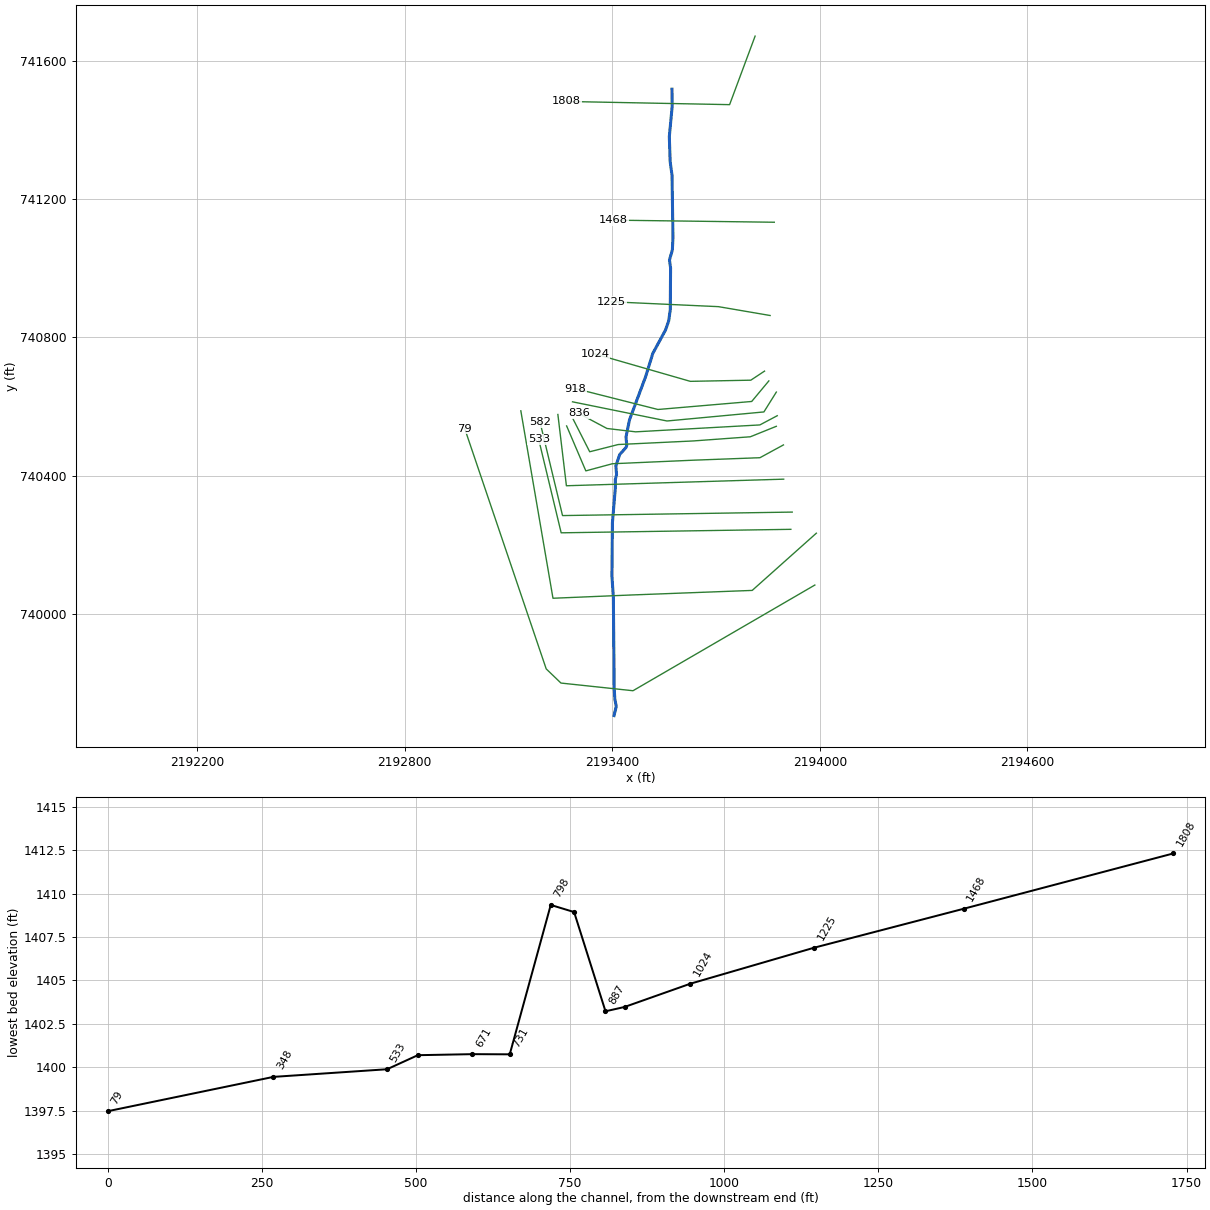
--- TURKEYRNT1.prj (project) ---

Proj Title=TURKEYRNT1
Current Plan=p01
Default Exp/Contr=0,0
English Units
Geom File=g01
Flow File=f01
Plan File=p01
BEGIN DESCRIPTION:
---------- MODELED AS PART OF WVEMD CTP PROGRAM, 2023----------
Stream Name: Turkey Run Tributary 1
Flood Zone:  AFH
Upshur County, WV
HEC-RAS Version: RAS 6.3
Vertical Datum: NAVD88
Projection: NAD 1983 StatePlane West Virginia S FIPS 4702 (US Feet)
Terrain: 1-meter LIDAR (FEMA Region III 3DEP collected 2016-2018)
Land Use: 2019 NLCD
Hydrologic Method:
WV SIR2010-5033 regression equations
Additional Model Notes:
None
END DESCRIPTION:
DSS Export Rating Curves= 0
DSS Export Rating Curve Sorted= 0
DSS Export Volume Flow Curves= 0
DXF OffsetX= 0
DXF OffsetY= 0
DXF ScaleX= 0
DXF ScaleY= 0

--- TURKEYRNT1.p01 (plan) ---

Plan Title=Floodplain
Program Version=6.30
Short Identifier=Floodplain
Geom File=g01
Flow File=f01
Subcritical Flow
K Sum by GR= 0
Std Step Tol= 0.01
Critical Tol= 0.01
Num of Std Step Trials= 20
Max Error Tol= 0.3
Flow Tol Ratio= 0.001
Split Flow NTrial= 30
Split Flow Tol= 0.02
Split Flow Ratio= 0.02
Log Output Level= 0
Friction Slope Method= 1
Unsteady Friction Slope Method= 2
Unsteady Bridges Friction Slope Method= 1
Parabolic Critical Depth
Global Vel Dist= 0 , 0 , 0
Global Log Level= 0
CheckData=True
Encroach Param=-1 ,0,0, 0
Mapping Interval=1HOUR
Computation Time Step Use Courant=        0
Computation Time Step Use Time Series=    0
Computation Time Step Count To Double=0
Computation Time Step Max Doubling=0
Computation Time Step Max Halving=0
Computation Time Step Residence Courant=0
Run HTab= 0
Run UNet= 0
Run Sediment= 0
Run PostProcess= 0
Run WQNet= 0
Run RASMapper= 0
UNET Theta= 0
UNET Theta Warmup= 0
UNET ZTol= 0
UNET ZSATol= 0
UNET MxIter= 0
UNET Max Iter WO Improvement= 0
UNET MaxInSteps= 0
UNET DtIC= 0
UNET DtMin= 0
UNET MaxCRTS= 0
UNET WFStab= 0
UNET SFStab= 0
UNET WFX= 1
UNET SFX= 1
UNET Gravity=32.17405
UNET 1D Methodology=Finite Difference
UNET DSS MLevel= 1
UNET Pardiso=0
UNET DZMax Abort= 0
UNET Use Existing IB Tables= 0
UNET Froude Reduction=False
UNET Froude Limit= 0
UNET Froude Power= 0
UNET D1 Cores= 0
UNET WindReference=Eulerian
UNET WindDragFormulation=Hsu (1988)
UNET D2 Coriolis=0
UNET D2 Cores= 0
UNET D2 Theta= 1
UNET D2 Theta Warmup= 1
UNET D2 Z Tol= 0.01
UNET D2 Volume Tol= 0.01
UNET D2 Max Iterations= 20
UNET D2 Equation= 0
UNET D2 RampUpFraction=0.1
UNET D2 TimeSlices= 1
UNET D2 Turbulence Formulation=Non-Conservative (original)
UNET D2 Eddy Viscosity=0.3
UNET D2 Transverse Eddy Viscosity=0.1
UNET D2 Smagorinsky Mixing=0
UNET D2 BCVolumeCheck=0
UNET D2 Cores=0
UNET D2 SolverType=PARDISO (Direct)
UNET D2 Minimum Iterations= 3
UNET D2 Maximum Iterations= 30
UNET D2 Restart Number= 10
UNET D2 Relaxation Coeff=1.3
UNET D2 SOR Precondition Iterations= 10
UNET D2 ILUT Maximum Fill= 8
UNET D2 ILUT Tolerance=1E-08
UNET D2 Convergence Tolerance=0.00001
UNET D1D2 MaxIter= 0
UNET D1D2 ZTol=0.01
UNET D1D2 QTol=0.1
UNET D1D2 MinQTol=1
Write IC File= 0
Write IC File at Fixed DateTime=0
Write IC File at Sim End=0
Echo Input=False
Echo Parameters=False
Echo Output=False
Write Detailed= 0
HDF Write Warmup=0
HDF Write Time Slices=0
HDF Flush=0
HDF Compression= 1
HDF Chunk Size= 1
HDF Spatial Parts= 1
HDF Use Max Rows=0
HDF Fixed Rows= 1
Calibration Method= 0
Calibration Iterations= 20
Calibration Max Change=0.05
Calibration Tolerance=0.2
Calibration Maximum=1.5
Calibration Minimum=0.5
Calibration Optimization Method= 1
WQ AD Non Conservative
WQ ULTIMATE=-1
WQ Max Comp Step=1HOUR
WQ Output Interval=15MIN
WQ Output Selected Increments= 0
WQ Output face flow=0
WQ Output face velocity=0
WQ Output face area=0
WQ Output face dispersion=0
WQ Output cell volume=0
WQ Output cell surface area=0
WQ Output cell continuity=0
WQ Output cumulative cell continuity=0
WQ Output face conc=0
WQ Output face dconc_dx=0
WQ Output face courant=0
WQ Output face peclet=0
WQ Output face adv mass=0
WQ Output face disp mass=0
WQ Output cell mass=0
WQ Output cell source sink temp=0
WQ Output nsm pathways=0
WQ Output nsm derived pathways=0
WQ Create Restart=0
WQ Fixed Restart=0
WQ System Summary=0
WQ Write To DSS=0
Sorting and Armoring Iterations= 10
XS Update Threshold= 0.02
Bed Roughness Predictor= 0
Hydraulics Update Threshold= 0.02
Energy Slope Method= 1
Volume Change Method= 1
Sediment Retention Method= 0
Sediment TS Multiplier= 1
Warm Up Method= 0
XS Weighting Method= 0
Number of US Weighted Cross Sections= 1
Number of DS Weighted Cross Sections= 1
Upstream XS Weight=0
Main XS Weight=1
Downstream XS Weight=0
Number of DS XS's Weighted with US Boundary= 1
Upstream Boundary Weight= 1
Weight of XSs Associated with US Boundary= 0
Number of US XS's Weighted with DS Boundary= 1
Downstream Boundary Weight= 0.5
Weight of XSs Associated with DS Boundary= 0.5
Percentile Method= 0
Sediment Output Level= 3
Mass or Volume Output= 0
Output Increment Type= 1
Profile and TS Output Increment= 1
Transport Output Increment 1
XS Output Flag= 0
XS Output Increment= 10
Read HDF5 Sediment Hotstart= 0
Sediment Hotstart Type= 0
Write Gradation File= 0
Read Gradation Hotstart= 0
Write HDF5 File= 1
Write Binary Output= 1
Write DSS Sediment File= 0
DSS Sediment Output Type= 1
SV Curve= 0
Specific Gage Flag= 0
Subcell Erosion Methods= 0
Subcell Deposition Methods= 0
Advection Scheme= 1
Matrix Solver= 0
Implicit Weighting Factor= 1
Maximum Outer Loop Convergence Iterations= 5
Convergence Maximum Absolute= 0.001
Convergence RMSE= 0.0001
Grain Fractions Max Abs Error= 0.001
Max Subgrid Regions= 1
Max Subgrid Length Scale= 3.402823E+38
Initial Layer Thickness= 3.402823E+38
Min Layer Thickness= 3.402823E+38
Max Layer Thickness= 3.402823E+38
Number of Layers= 5

--- TURKEYRNT1.f01 (steady flow) ---

Flow Title=Flows
Program Version=6.30
Number of Profiles= 1
Profile Names=01pct
River Rch & RM=TURKEYRNT1,Main            ,1808
    97.3
River Rch & RM=TURKEYRNT1,Main            ,1024
     110
Boundary for River Rch & Prof#=TURKEYRNT1,Main            , 1
Up Type= 0
Dn Type= 3
Dn Slope=0.0053
DSS Import GetInterval= 0
DSS Import GetPeak= 0
DSS Import FillOption= 0

--- TURKEYRNT1.g01 (geometry) ---

Geom Title=Geometry
Program Version=6.30

River Reach=TURKEYRNT1      ,Main
Reach XY= 30
 2193572.6493555741517.6958940332193573.19131176  741467.6066349
2193564.96077129741380.4473219222193567.40100002741308.295000002
2193572.81000003741268.6899999982193575.49973436741088.550014958
2193573.78383537741053.2515216922193565.44946891741024.081239074
2193568.63613839741001.0391671062193567.71600004740880.079999998
2193563.13800001740847.772000015     2193553.866740821.330000013
2193517.23700003740753.9669999932193496.40400003740686.547000006
2193449.99090128 740562.385897072193439.82231076740512.735690117
2193441.91020238740487.9409742062193439.66609199740481.971517146
2193421.59767579740461.7190066432193410.47865039740428.957592592
2193412.46419063740403.542677447 2193408.8902182740390.041003764
2193408.86700004740364.1550000012193400.49098973740264.031301558
2193399.12916516740109.8727584632193403.21782458740048.184905261
2193405.66592318739784.9414123892193407.57247759739753.891811863
2193411.65795136739733.7368079872193405.11904307739707.079206347

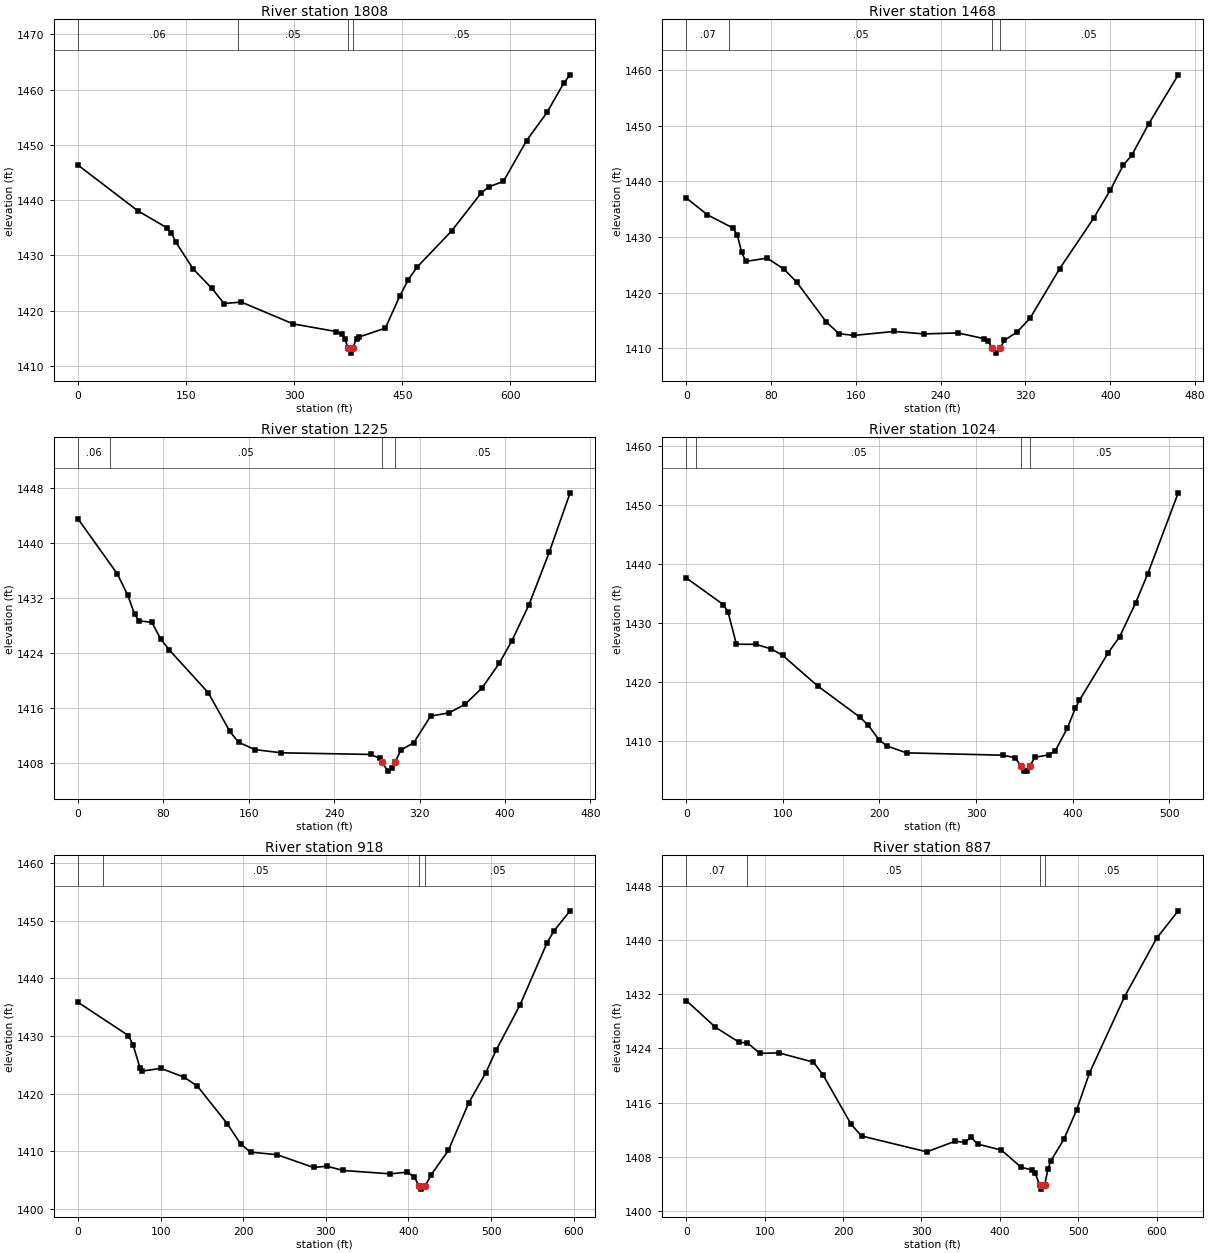
Type RM Length L Ch R = 1 ,1808    ,340.2,340.2,340.2
XS GIS Cut Line= 3
2193812.93190922741671.0554963212193739.21514483741472.941692026
2193267.73500593741482.156287575
#Sta/Elev= 30
       0 1446.32    83.1 1438.05   123.4 1434.99   129.6 1434.02   135.8 1432.36
   159.9 1427.52   185.7 1424.04   202.6 1421.29   226.5 1421.56   298.4 1417.61
   358.5 1416.22   366.5 1415.73   370.5 1414.91   374.5 1413.22   378.5 1412.32
  381.111413.218   386.5 1414.94   389.7 1415.22   426.5 1416.84   446.8 1422.72
   458.5 1425.64   470.5 1427.88   518.5 1434.43   559.9 1441.36   570.5 1442.42
   590.5 1443.41   622.5 1450.77   650.9 1455.87   674.5 1461.25     683 1462.68
#Mann= 4 ,-1,0
       0     .06       0  221.38     .05       0   374.5    .045       0
  381.11     .05       0
Bank Sta=374.5,381.11
XS Rating Curve= 0 ,0
Exp/Cntr(USF)=0,0
Exp/Cntr=0.3,0.1

Type RM Length L Ch R = 1 ,1468    ,243.3,243.1,242.7
XS GIS Cut Line= 2
2193868.35218137741133.0636194992193404.32306339741139.116173212
#Sta/Elev= 30
       0    1437      20 1433.97    44.2 1431.59    48.2 1430.33    52.2 1427.29
    56.2  1425.6    76.2  1426.2    92.2 1424.21   104.2 1421.88   132.2  1414.7
   144.2 1412.62   158.1 1412.31   196.2 1413.03   224.2 1412.58   256.2 1412.76
   280.7 1411.74   284.2 1411.38  288.71 1410.08   292.2 1409.13   296.2 1410.06
   300.2 1411.43   312.2 1412.94   324.2 1415.37   352.2 1424.28   384.2 1433.33
   400.2 1438.48   412.2 1442.88   420.2 1444.67   436.2  1450.3   464.1 1459.12
#Mann= 4 ,-1,0
       0     .07       0      40     .05       0  288.71    .045       0
   296.2     .05       0
Bank Sta=288.71,296.2
XS Rating Curve= 0 ,0
Exp/Cntr(USF)=0,0
Exp/Cntr=0.3,0.1

Type RM Length L Ch R = 1 ,1225    ,203.1,200.3,197.5
XS GIS Cut Line= 3
2193856.32456434740863.5187994672193707.02823942740889.074026255
2193397.67549411740903.196651585
#Sta/Elev= 30
       0 1443.46    36.7 1435.51    46.6 1432.38    52.9 1429.65      57 1428.69
    69.1 1428.47    77.3 1426.08    85.4 1424.47   121.9 1418.27   142.2 1412.64
   150.3 1411.07   165.8    1410   190.4 1409.54   274.4  1409.3   282.5 1408.74
  284.67 1408.14   290.5 1406.88   294.5 1407.31     297 1408.15   302.5 1409.94
   314.5    1411   330.4 1414.87   347.4 1415.33   362.5 1416.56   378.6 1418.96
   394.6 1422.51   406.6 1425.82   422.6 1431.04   441.5 1438.63   461.1 1447.27
#Mann= 4 ,-1,0
       0     .06       0      30     .05       0  284.67    .045       0
     297     .05       0
Bank Sta=284.67,297
XS Rating Curve= 0 ,0
Exp/Cntr(USF)=0,0
Exp/Cntr=0.3,0.1

Type RM Length L Ch R = 1 ,1024    ,106.2,106.6,106.6
XS GIS Cut Line= 4
2193840.18442111740702.7898730952193800.50656899 740676.56214034
2193625.65501729740673.1996104992193349.92757037740752.555314733
#Sta/Elev= 30
       0 1437.58    38.4 1433.06    43.2 1431.83    51.9 1426.34    71.9 1426.32
    87.9 1425.55    99.9 1424.44   135.9 1419.28   179.9 1413.95   188.6 1412.56
   199.9 1410.06   207.9 1409.07   228.1 1407.91     328 1407.51   340.5 1407.08
   346.4 1405.73   349.7 1404.81     353 1404.91  355.66 1405.73   361.3 1407.16
   375.5 1407.58   382.2  1408.3   394.6 1412.11     403 1415.54   407.1 1416.82
   436.9 1424.89   448.8 1427.63   465.4  1433.4   477.9 1438.31   509.4 1452.02
#Mann= 4 ,-1,0
       0     .07       0      10     .05       0   346.4    .045       0
  355.66     .05       0
Bank Sta=346.4,355.66
XS Rating Curve= 0 ,0
Exp/Cntr(USF)=0,0
Exp/Cntr=0.3,0.1

Type RM Length L Ch R = 1 ,918     ,30.7,31,31.5
XS GIS Cut Line= 4
2193852.62279788740674.4424376052193803.09310937740615.039842256
2193532.04439912740591.8646737212193293.23940161740652.321635115
#Sta/Elev= 30
       0 1435.83    60.9 1430.08    66.5 1428.48    75.1 1424.38    77.3 1423.92
   100.3  1424.4   128.4 1422.86   144.5 1421.31   180.6  1414.8   196.7 1411.31
   208.7 1409.88   240.8 1409.44     285 1407.22   301.1 1407.44   321.1  1406.7
   378.1 1406.12   398.8 1406.42     407 1405.54413.14941403.967   415.3 1403.47
   419.9 1403.94   427.6 1405.98   448.3 1410.19     473 1418.44   493.7 1423.66
     506 1427.52   534.9 1435.34   567.9 1446.19   576.2 1448.23   595.7  1451.7
#Mann= 4 ,-1,0
       0     .07       0      30     .05       0413.1494    .045       0
   419.9     .05       0
Bank Sta=413.1494,419.9
XS Rating Curve= 0 ,0
Exp/Cntr(USF)=0,0
Exp/Cntr=0.3,0.1

Type RM Length L Ch R = 1 ,887     ,50.1,50.9,51.8
XS GIS Cut Line= 4
2193874.29340195740642.1947860742193838.35967018740584.804626512
2193558.24241572740558.6066099082193285.17847342740614.025491186
#Sta/Elev= 30
       0 1431.09    37.1 1427.15    67.7  1424.9    77.9 1424.84      94 1423.28
   118.1 1423.35   162.3 1421.98   174.4 1420.11   210.5 1412.78   223.7 1411.07
   306.9 1408.73   343.1  1410.3   355.2 1410.14   363.4 1410.88   371.6 1409.88
   402.2 1408.98   427.6 1406.42     441 1406.08     445 1405.62   450.8 1403.87
   453.2 1403.22   457.3 1403.87   461.6 1406.22   465.4 1407.44   481.8 1410.58
   498.1 1414.92   514.4 1420.37   559.3 1431.67   600.1 1440.28   627.7 1444.34
#Mann= 4 ,-1,0
       0     .07       0   77.71     .05       0   450.8    .045       0
   457.3     .05       0
Bank Sta=450.8,457.3
XS Rating Curve= 0 ,0
Exp/Cntr(USF)=0,0
Exp/Cntr=0.3,0.1

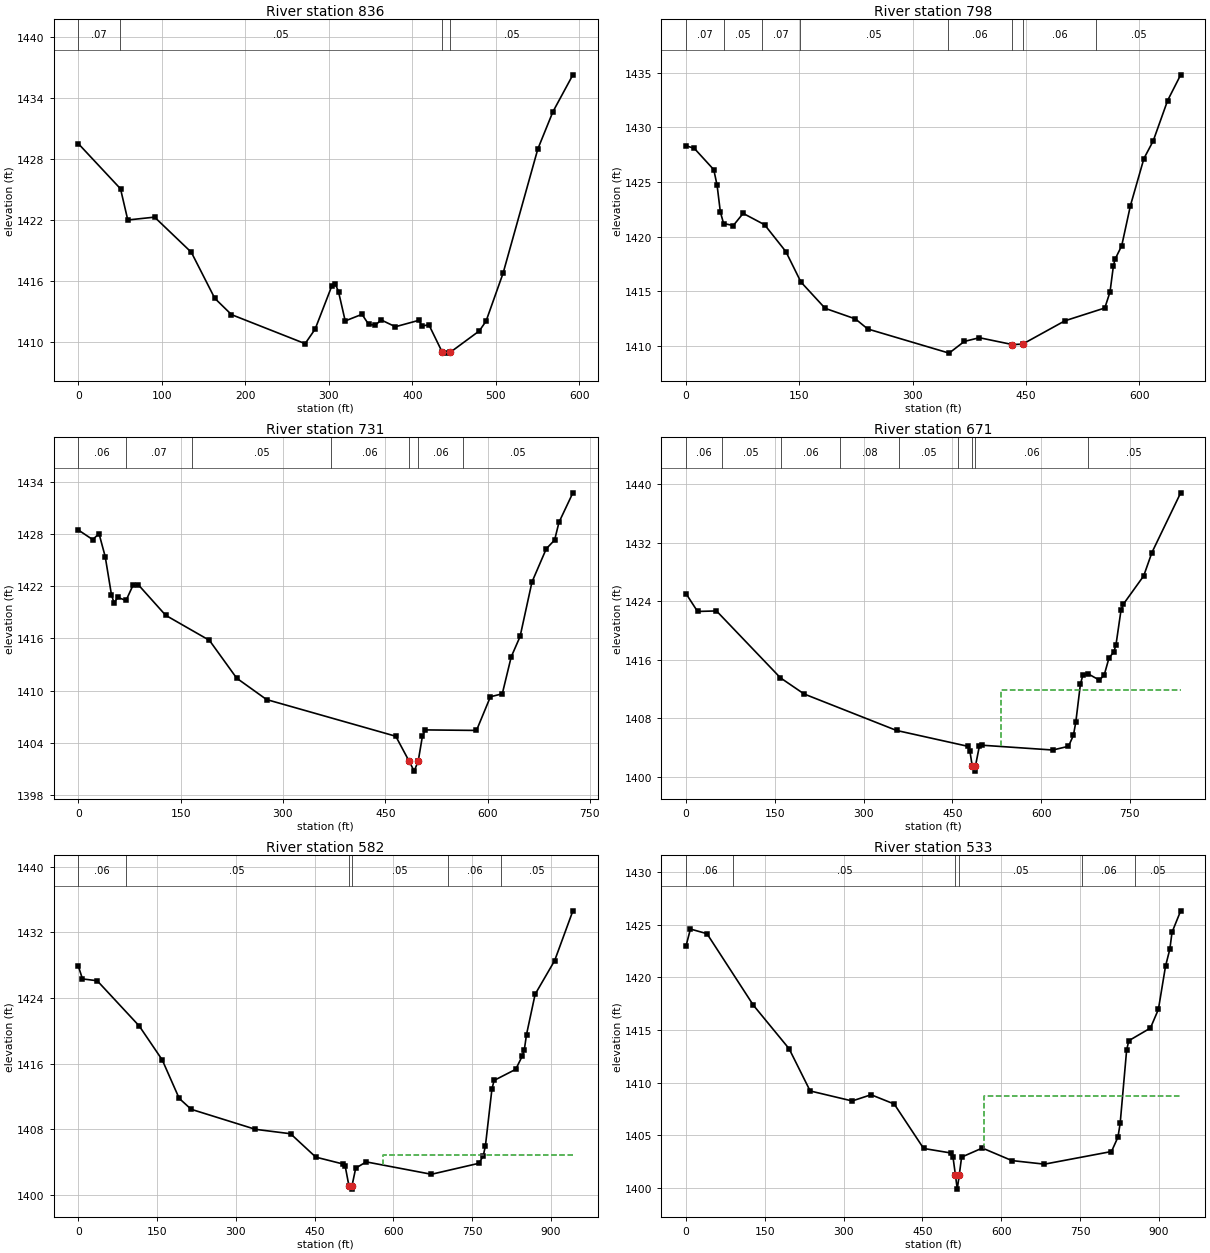
Type RM Length L Ch R = 1 ,836     ,35.6,37.9,40.1
XS GIS Cut Line= 5
2193876.87365506740573.8634679772193826.63745925 740547.23223164
2193467.72102408740527.2588043882193384.80103821740536.942890329
2193303.09156309740580.521277061
#Sta/Elev= 30
       0 1429.51    50.6 1425.07    59.3 1422.01    91.4 1422.29   135.4 1418.84
   163.5 1414.32   183.5 1412.72   271.7 1409.87   283.7  1411.3   303.7 1415.54
   307.7 1415.76   311.7 1414.97   319.7  1412.1   339.8 1412.75   347.8 1411.76
   355.8 1411.68   362.7  1412.2   379.8 1411.53   407.9 1412.16   411.9  1411.6
   419.9 1411.73     436 1409.02     440 1408.94   445.5 1409.02   480.3 1411.12
   488.4 1412.08   508.8 1416.79   550.4 1428.98   568.5 1432.64   592.4 1436.26
#Mann= 4 ,-1,0
       0     .07       0      50     .05       0     436    .045       0
   445.5     .05       0
Bank Sta=436,445.5
XS Rating Curve= 0 ,0
Exp/Cntr(USF)=0,0
Exp/Cntr=0.3,0.1

Type RM Length L Ch R = 1 ,798     ,66.4,66.5,65
XS GIS Cut Line= 6
2193874.25661176740543.2498864042193799.18062778740512.988166509
2193633.60760047740500.8993277142193417.29538333740490.576697356
2193334.87775943740469.6590717252193286.61469612740564.632718309
#Sta/Elev= 30
       0 1428.33    10.9 1428.09    36.7 1426.14    41.1 1424.71    45.4 1422.28
    49.7 1421.21    62.6 1421.03    75.6 1422.14     104  1421.1   132.2 1418.64
   152.1 1415.86   184.2 1413.45   224.3 1412.48   240.6 1411.56   348.4 1409.35
   368.5 1410.42   388.5 1410.76432.21571410.134445.78321410.175   501.8 1412.31
   554.6 1413.48   561.5 1414.95     566 1417.34   568.1 1417.93     577 1419.18
   588.5 1422.84   606.4 1427.16   618.7 1428.77   637.8 1432.47   655.1 1434.82
#Mann= 8 ,-1,0
       0     .07       0      50     .05       0  100.95     .07       0
  150.95     .05       0  346.96     .06       0432.2157    .045       0
445.7832     .06       0  543.58     .05       0
Bank Sta=432.2157,445.7832
XS Rating Curve= 0 ,0
Exp/Cntr(USF)=0,0
Exp/Cntr=0.3,0.1

Type RM Length L Ch R = 1 ,731     ,60.8,60.5,60.1
XS GIS Cut Line= 6
2193894.83605382 740489.472769512193826.87916828740452.481519684
 2193634.4551931740445.2952493962193400.15440086740435.005996663
2193323.64709566 740414.387972442193268.16636204740544.306037885
#Sta/Elev= 30
       0 1428.47    21.2 1427.36    30.4 1428.05    39.5  1425.4    48.6 1421.04
    52.3 1420.11    58.2 1420.71      70 1420.36    80.1 1422.09    88.1 1422.16
   128.1 1418.66   192.2 1415.78   232.2 1411.43     276 1408.97   465.4 1404.75
  484.75 1401.91   492.4 1400.74  498.321401.913   504.4 1404.74   508.6 1405.48
   583.7 1405.42   604.1 1409.29   621.5 1409.63   634.6 1413.88   647.6 1416.22
     665 1422.48     686 1426.31   698.2 1427.31   704.6 1429.35     725 1432.74
#Mann= 7 ,-1,0
       0     .06       0      70     .07       0  167.37     .05       0
  369.93     .06       0  484.75    .045       0  498.32     .06       0
  564.46     .05       0
Bank Sta=484.75,498.32
XS Rating Curve= 0 ,0
Exp/Cntr(USF)=0,0
Exp/Cntr=0.3,0.1

Type RM Length L Ch R = 1 ,671     ,88.7,88.6,88.6
XS GIS Cut Line= 3
2193895.58608218740390.468489168 2193267.5054277740371.435742062
2193242.87481379740577.437240147
#Sta/Elev= 30
       0 1425.04    19.4 1422.61    51.4 1422.68   159.5 1413.52   199.5 1411.31
   355.6 1406.32   475.6 1404.16   479.6 1403.52   483.6 1401.42   487.6 1400.75
  488.891401.405   495.6 1404.16   499.6  1404.3   619.7 1403.64   646.2 1404.15
   654.5 1405.64   658.6 1407.48   666.4 1412.68   670.4 1413.85   678.5 1414.11
   698.6  1413.2   706.7 1413.95   714.7 1416.25   722.8 1417.06   726.5 1418.06
   734.9 1422.75   738.9  1423.6   773.3 1427.48   787.2 1430.68   835.8 1438.85
#Mann= 9 ,-1,0
       0     .06       0      60     .05       0     160     .06       0
     260     .08       0     360     .05       0     460     .06       0
   483.6    .045       0  488.89     .06       0  678.37     .05       0
#XS Ineff= 2 , 0
                          531.35         1411.84
Permanent Ineff=
       F       F
Bank Sta=483.6,488.89
XS Rating Curve= 0 ,0
Exp/Cntr(USF)=0,0
Exp/Cntr=0.3,0.1

Type RM Length L Ch R = 1 ,582     ,49.8,49.9,49.9
XS GIS Cut Line= 3
2193920.21669608 740295.30475364 2193256.3096941740285.228593407
2193191.37443927740555.045772964
#Sta/Elev= 30
       0 1427.89       8 1426.31      36 1426.09   116.1 1420.57   159.8 1416.44
   192.1 1411.75   214.9 1410.42   337.1 1407.98   404.1 1407.44   452.1 1404.59
   504.1 1403.75   508.1 1403.48  515.211401.086   520.1 1400.69  520.941401.064
   528.1 1403.25   548.1 1404.01   672.2  1402.5   762.7 1403.84   770.9 1404.75
     775 1405.97   787.4 1412.89   791.5 1413.94   832.6 1415.29     845 1416.89
   849.1  1417.7   853.2 1419.53   869.6 1424.44   906.7 1428.53   941.5 1434.61
#Mann= 6 ,-1,0
       0     .06       0      90     .05       0  515.21    .045       0
  520.94     .05       0  703.98     .06       0  803.98     .05       0
#XS Ineff= 2 , 0
                          579.44         1404.87
Permanent Ineff=
       F       F
Bank Sta=515.21,520.94
XS Rating Curve= 0 ,0
Exp/Cntr(USF)=0,0
Exp/Cntr=0.3,0.1

Type RM Length L Ch R = 1 ,533     ,184,184.3,184.5
XS GIS Cut Line= 3
2193916.29818932740245.4837391582193252.39118735740235.407578925
2193187.45593252740505.224758481
#Sta/Elev= 30
       0 1422.98     8.3 1424.57    39.8 1424.13   128.1 1417.34   196.1 1413.21
   236.2  1409.2   316.2 1408.25   352.2 1408.84   396.2 1407.96   452.2 1403.74
   504.2 1403.31   508.2 1402.89   512.7 1401.22   516.2 1399.88  519.89 1401.18
   524.5 1402.92   563.9 1403.78   620.2 1402.59   682.2 1402.25   809.8 1403.45
   822.1 1404.82   826.3 1406.12   838.6 1413.07   842.7 1413.97   883.9 1415.17
   899.1 1416.95   912.7 1421.06   920.9 1422.67     925 1424.26   941.5  1426.3
#Mann= 6 ,-1,0
       0     .06       0      90     .05       0   512.7    .045       0
  519.89     .05       0  753.98     .06       0  853.98     .05       0
#XS Ineff= 2 , 0
                          567.22         1408.76
Permanent Ineff=
       F       F
Bank Sta=512.7,519.89
XS Rating Curve= 0 ,0
Exp/Cntr(USF)=0,0
Exp/Cntr=0.3,0.1

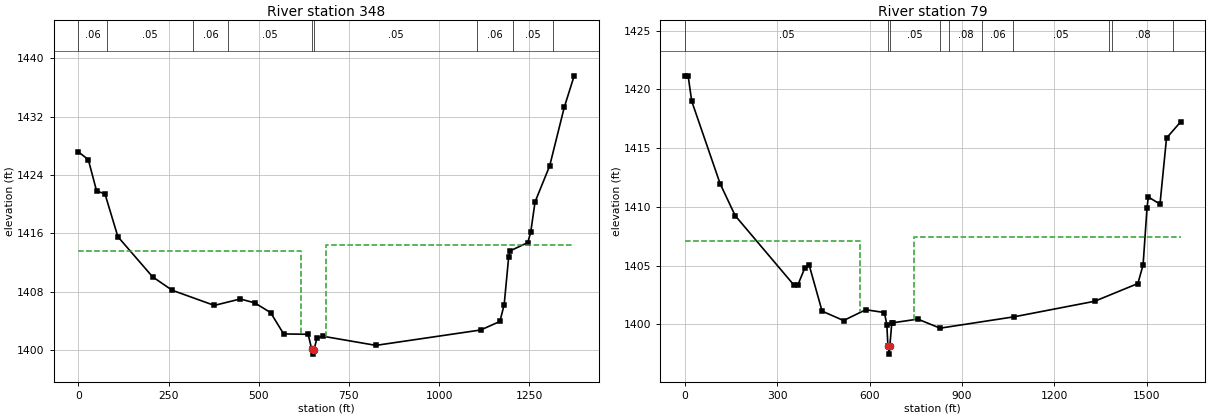
Type RM Length L Ch R = 1 ,348     ,268.9,268.9,268.9
XS GIS Cut Line= 6
2193989.95512486740234.341054633 2193804.5099396740068.910015166
2193614.02081926740061.716788083 2193451.6363015740055.584254429
2193228.69251694740046.281882589 2193135.7776832740588.034104599
#Sta/Elev= 30
       0 1427.17    27.6 1426.12    50.6 1421.81    73.9 1421.41   109.6 1415.54
     206 1410.03   260.1  1408.2   376.9 1406.12   448.8    1407     489 1406.47
     533 1405.13   569.1 1402.21   637.1 1402.16     6471400.076   649.1 1399.44
  653.35 1400.05   661.1 1401.59   677.2  1401.9   824.8 1400.64  1115.3 1402.75
  1168.6 1403.92  1180.4 1406.23    1193 1412.81    1197  1413.6  1245.7 1414.73
  1253.9 1416.13    1266 1420.31  1306.6 1425.26  1346.9 1433.27  1374.4  1437.6
#Mann= 9 ,-1,0
       0     .06       0      80     .05       0  318.51     .06       0
  415.39     .05       0     647    .045       0  653.35     .05       0
 1104.77     .06       0 1204.77     .05       0 1314.77     .07       0
#XS Ineff= 2 , 0
          616.01 1413.52  685.41          1414.4
Permanent Ineff=
       F       F
Bank Sta=647,653.35
XS Rating Curve= 0 ,0
Exp/Cntr(USF)=0,0
Exp/Cntr=0.3,0.1

Type RM Length L Ch R = 1 ,79      ,,,
XS GIS Cut Line= 5
2193985.52684844740084.4188373522193459.95362085739778.972058982
2193251.77201772739801.1553445622193209.11185314739842.109102556
2192973.62774468740536.616581867
#Sta/Elev= 30
       0 1421.13    10.8 1421.15    22.4    1419   114.5 1411.98   163.5 1409.25
   353.2 1403.37   367.1 1403.35   390.2 1404.83   404.1 1405.01   445.7 1401.12
   515.4 1400.32   587.6 1401.24   647.9    1401   655.9 1399.98  659.41 1398.15
     664 1397.46  665.461398.113     672  1400.1     676 1400.13   756.5 1400.44
   828.8 1399.67  1069.7 1400.64  1330.6 1401.96  1470.9 1403.47  1487.8 1405.05
  1500.5 1409.86  1504.7 1410.84  1542.7 1410.23  1563.9 1415.85  1609.7 1417.23
#Mann= 10 ,-1,0
       0     .05       0  659.41    .045       0  665.46     .05       0
  827.25     .07       0  857.25     .08       0  966.38     .06       0
 1066.38     .05       0 1376.38     .07       0 1386.38     .08       0
 1586.38     .07       0
#XS Ineff= 2 , 0
          569.37  1407.1  745.36         1407.41
Permanent Ineff=
       F       F
Bank Sta=659.41,665.46
XS Rating Curve= 0 ,0
Exp/Cntr(USF)=0,0
Exp/Cntr=0.3,0.1
LCMann Table=0

Chan Stop Cuts=-1
Use User Specified Reach Order=0
Composite Channel Slope=5